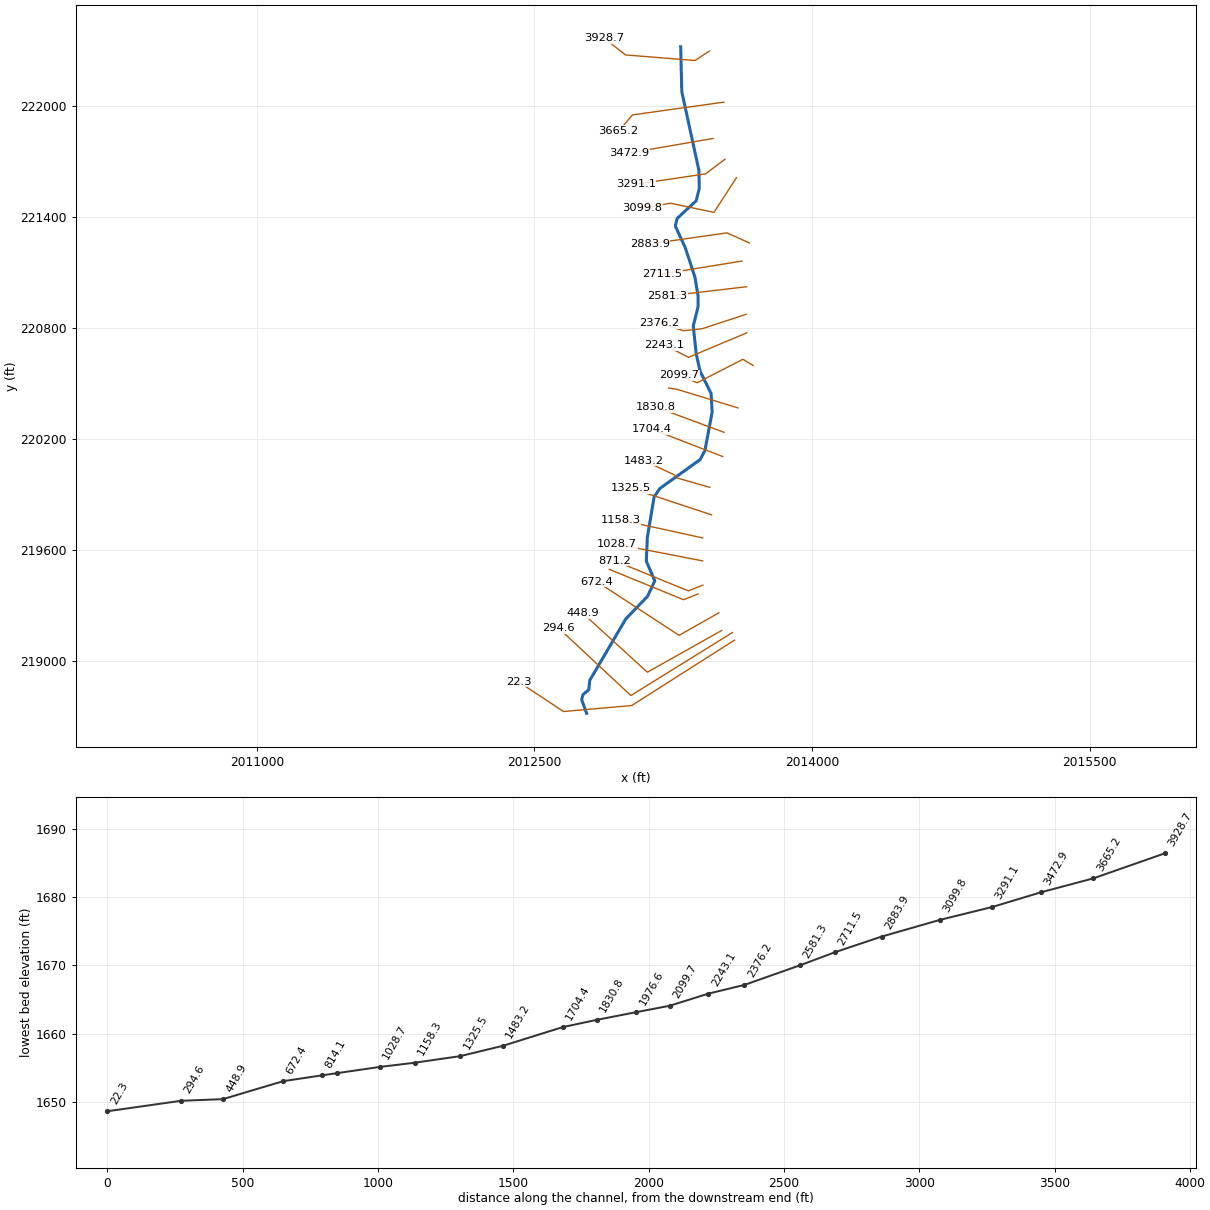
--- WOLFCKTRIB.prj (project) ---

Proj Title=WOLFCKTRIB
Current Plan=p01
Default Exp/Contr=0,0
English Units
Geom File=g01
Flow File=f01
Plan File=p01
BEGIN DESCRIPTION:
END DESCRIPTION:
DSS Export Rating Curves= 0
DSS Export Rating Curve Sorted= 0
DSS Export Volume Flow Curves= 0
DXF OffsetX= 0
DXF OffsetY= 0
DXF ScaleX= 0
DXF ScaleY= 0

--- WOLFCKTRIB.p01 (plan) ---

Plan Title=Floodplain
Program Version=4.00
Geom File=g01
Flow File=f01
K Sum by GR=0
Std Step Tol=0.01
Critical Tol=0.01
Num of Std Step Trials=20
Max Error Tol=0.3
Flow Tol Ratio=0.001
Split Flow NTrial=30
Split Flow Tol=0.02
Split Flow Ratio=0.02
Log Output Level=0
Friction Slope Method=1
Unsteady Friction Slope Method=2
Unsteady Bridges Friction Slope Method=1
Global Log Level=0
CheckData=False
Run HTab=0
Run UNet=0
Run PostProcess=0
UNET Theta=0
UNET Theta Warmup=0
UNET ZTol=0
UNET ZSATol=0
UNET MxIter=0
UNET MaxInSteps=0
UNET DtIC=0
UNET DtMin=0
UNET MaxCRTS=0
UNET WFStab=0
UNET SFStab=0
UNET WFX=0
UNET SFX=0
UNET DSS MLevel=0
UNET DZMax Abort=0
UNET Convert EG Bridges=0
UNET Use Existing IB Tables=0
UNET Froude Limit=0
UNET Froude Power=0
Write IC File=0
Echo Input=False
Echo Output=False
Write Detailed=0

--- WOLFCKTRIB.f01 (steady flow) ---

Flow Title=NFF Regression Equation
Program Version=4.00
Number of Profiles=1
Profile Names=P100yr
River Rch & RM=WOLFCKTRIB,Main      ,3928.7
496.6248
River Rch & RM=WOLFCKTRIB,Main      ,3472.9
537.9497
River Rch & RM=WOLFCKTRIB,Main      ,2883.9
579.0719
River Rch & RM=WOLFCKTRIB,Main      ,448.9
611.5914
River Rch & RM=WOLFCKTRIB,Main      ,294.6
613.6538
Boundary for River Rch & Prof#=WOLFCKTRIB,Main      ,1
Up Type=0
Dn Type=3
Dn Slope=0.007732

--- WOLFCKTRIB.g01 (geometry) ---

Geom Title=USGS 10m DEM
Program Version=4.10

River Reach=WOLFCKTRIB      ,Main
Reach XY= 30
     2013290.617      222320.621     2013296.623      222077.983
     2013388.984      221652.288     2013391.067      221554.372
     2013374.401      221487.705     2013270.928      221391.177
     2013261.901      221350.205     2013314.678      221235.622
     2013367.456      221075.205     2013384.817      220972.428
     2013384.817      220915.483     2013358.667      220810.129
     2013374.401      220660.622     2013395.541      220565.139
     2013454.956      220445.344     2013460.512      220343.955
     2013421.898      220137.525     2013395.929      220087.705
     2013177.815      219931.079     2013147.259      219886.634
     2013110.454      219666.496     2013104.898      219538.024
     2013150.731      219431.773     2013111.843       219348.44
     2012993.787      219225.524     2012799.343      218893.579
     2012793.787       218842.19     2012762.954      218816.912
     2012755.593      218789.412       2012782.4       218715.02

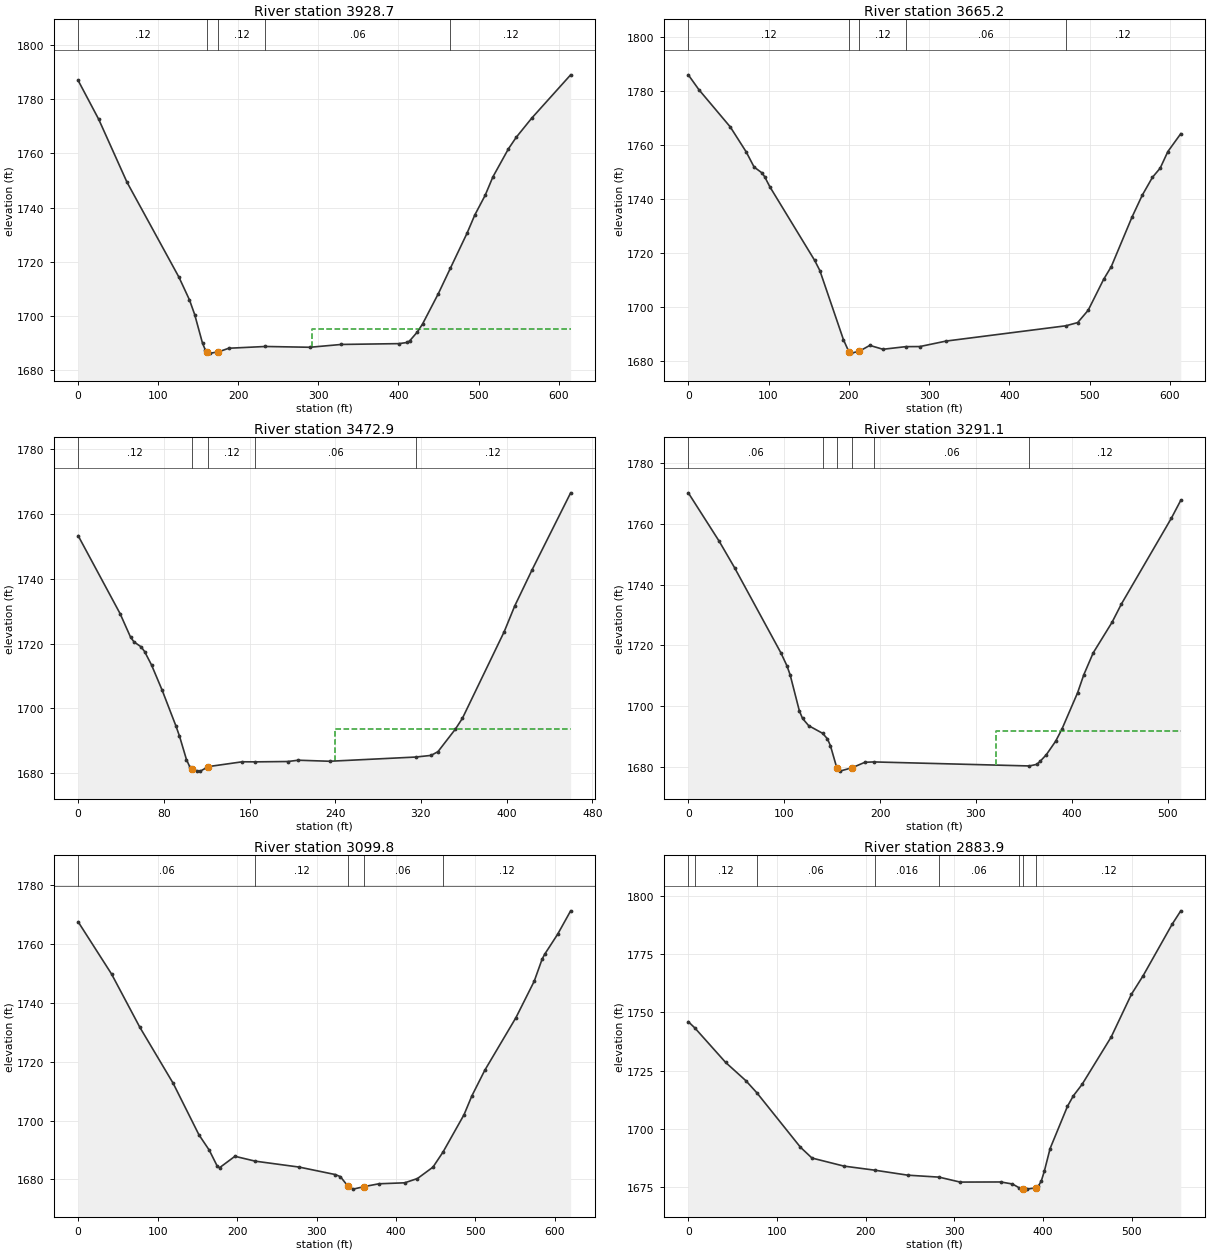
Type RM Length L Ch R = 1 ,3928.7  ,258.5,263.6,268.3
XS GIS Cut Line= 4
     2013445.921      222297.005     2013367.796      222246.223
     2012992.796      222276.171     2012878.212      222366.015
#Sta/Elev= 30
       0 1786.89    25.7 1772.56      61 1749.38   125.9 1714.36     139 1706.02
   145.5 1700.62   155.3 1690.03   158.6 1687.71  160.84 1686.96   165.2  1686.4
     175 1686.84     188  1688.2  233.79 1688.85   289.4 1688.56   328.7  1689.6
   400.7  1689.9   410.5 1690.32   413.8 1690.87   423.6 1694.21   430.1 1697.17
   449.8 1708.35  464.691717.634   485.6  1730.6   495.3 1737.32   508.2 1744.55
   517.9 1751.37   537.3 1761.71     547 1765.94   566.4 1773.02     615 1788.98
#Mann= 5 ,-1 , 0
       0     .12       0  160.84    .045       0     175     .12       0
  233.79     .06       0  464.69     .12       0
#XS Ineff= 2 , 0
                           292.1         1695.33
Permanent Ineff=
       F       F
Bank Sta=160.84,175
XS Rating Curve= 0 ,0
Exp/Cntr=0.3,0.1

Type RM Length L Ch R = 1 ,3665.2  ,191.2,192.3,192.7
XS GIS Cut Line= 3
     2013524.046      222020.963     2013030.556      221951.952
     2012955.035      221864.713
#Sta/Elev= 30
       0 1786.08    13.1 1780.61    52.4  1766.7    72.1 1757.49      82 1751.84
    91.8 1749.67    95.1 1748.28   101.6 1744.52   157.4 1717.21   163.9 1713.42
   193.4 1687.68     200 1683.32   203.2 1682.74   213.1 1683.45   226.2 1685.61
   242.6 1684.17  271.081685.149   288.5 1685.18   321.3 1687.22  470.391692.887
   485.2 1694.08   498.3 1698.66   517.5 1710.11   527.1 1714.88   552.8 1733.18
   565.6 1741.34   578.4 1748.03     588 1751.42   597.6 1757.59   613.7 1764.23
#Mann= 5 ,-1 , 0
       0     .12       0     200    .045       0   213.1     .12       0
  271.08     .06       0  470.39     .12       0
Bank Sta=200,213.1
XS Rating Curve= 0 ,0
Exp/Cntr=0.3,0.1

Type RM Length L Ch R = 1 ,3472.9  ,182.1,181.8,181
XS GIS Cut Line= 2
     2013465.452      221824.348     2013012.327      221746.223
#Sta/Elev= 30
       0 1753.21    39.1 1729.24    48.9 1721.98    52.2 1720.48    58.7 1719.01
      62 1717.55    68.5  1713.4    78.3 1705.72    91.3  1694.6    94.6 1691.49
   101.1 1684.28   104.4 1681.88   106.5 1681.35   110.9 1680.71   114.1 1680.71
   121.5  1682.1   153.3 1683.59  165.481683.565   195.7 1683.67   205.4 1684.07
   234.8 1683.75  315.091685.046   329.4 1685.55   335.9  1686.7   352.2 1693.66
   358.7 1696.96   397.8 1723.69   407.6 1731.59   423.9 1742.79   459.8 1766.42
#Mann= 5 ,-1 , 0
       0     .12       0   106.5    .045       0   121.5     .12       0
  165.48     .06       0  315.09     .12       0
#XS Ineff= 2 , 0
                          239.35         1693.76
Permanent Ineff=
       F       F
Bank Sta=106.5,121.5
XS Rating Curve= 0 ,0
Exp/Cntr=0.3,0.1

Type RM Length L Ch R = 1 ,3291.1  ,197.6,191.4,185.2
XS GIS Cut Line= 3
     2013530.556      221712.369     2013425.087      221632.942
     2013047.483      221576.952
#Sta/Elev= 30
       0  1770.2    32.2 1754.27    48.3 1745.53    96.6  1717.5     103 1713.17
   106.3 1710.19   115.9 1698.35   119.2 1695.89   125.6 1693.51  140.051691.011
   145.1 1689.21   148.3 1686.91   154.9 1679.64   158.1 1678.54   171.2 1679.69
   184.2 1681.45  193.431681.573  355.821680.243   363.7 1680.78   366.9 1681.72
   373.5 1683.94   383.3 1688.42   389.8 1692.38   406.1 1704.32   412.6 1710.27
   422.4 1717.48     442 1727.52   451.8 1733.56     504 1761.87   513.8 1767.75
#Mann= 6 ,-1 , 0
       0     .06       0  140.05     .12       0   154.9    .045       0
   171.2     .12       0  193.43     .06       0  355.82     .12       0
#XS Ineff= 2 , 0
                          321.31         1691.64
Permanent Ineff=
       F       F
Bank Sta=154.9,171.2
XS Rating Curve= 0 ,0
Exp/Cntr=0.3,0.1

Type RM Length L Ch R = 1 ,3099.8  ,208.9,215.8,221
XS GIS Cut Line= 4
     2013591.754      221612.109      2013470.66      221424.609
     2013236.285      221474.088     2013081.337      221448.046
#Sta/Elev= 30
       0 1767.61      42 1749.87    77.6 1731.75   119.7 1712.62     152 1695.16
     165 1689.93   174.7 1684.68   177.9 1683.94   197.3 1687.84  222.991686.181
   278.2 1684.17   323.6 1681.63     330 1680.93   339.7 1677.63   346.2 1676.67
   359.2 1677.49   378.6 1678.49     411 1678.82   427.1 1680.28   446.6 1684.16
   459.21689.274   485.7    1702   495.5 1708.37   511.8 1717.11   551.1 1735.06
     574  1747.4   583.9 1754.87   587.1 1756.55   603.5 1763.39   619.9 1771.36
#Mann= 5 ,-1 , 0
       0     .06       0  222.99     .12       0   339.7    .045       0
   359.2     .06       0   459.2     .12       0
Bank Sta=339.7,359.2
XS Rating Curve= 0 ,0
Exp/Cntr=0.3,0.1

Type RM Length L Ch R = 1 ,2883.9  ,171.7,172.4,173.1
XS GIS Cut Line= 3
     2013662.066      221259.244     2013540.973      221313.932
     2013123.004      221254.036
#Sta/Elev= 30
       0 1745.99    7.231743.362    42.1 1728.52    64.8 1720.73   77.241715.534
   126.4 1692.18   139.4 1687.54   175.4 1684.09  210.181682.342   247.4  1680.2
  282.641679.358   306.4 1677.24   352.2 1677.29   365.3 1676.42  372.741674.839
   377.1 1674.38   381.6 1674.22   392.1  1674.8   394.7 1675.58     398 1677.84
   401.3 1681.93   407.8 1691.62   427.4 1709.74     434 1714.21   443.8 1719.09
   476.6 1739.39   499.5 1757.76   512.6 1765.66   545.3 1787.72   555.1  1793.5
#Mann= 8 ,-1 , 0
       0     .06       0    7.23     .12       0   77.24     .06       0
  210.18    .016       0  282.64     .06       0  372.74     .12       0
   377.1    .045       0   392.1     .12       0
Bank Sta=377.1,392.1
XS Rating Curve= 0 ,0
Exp/Cntr=0.3,0.1

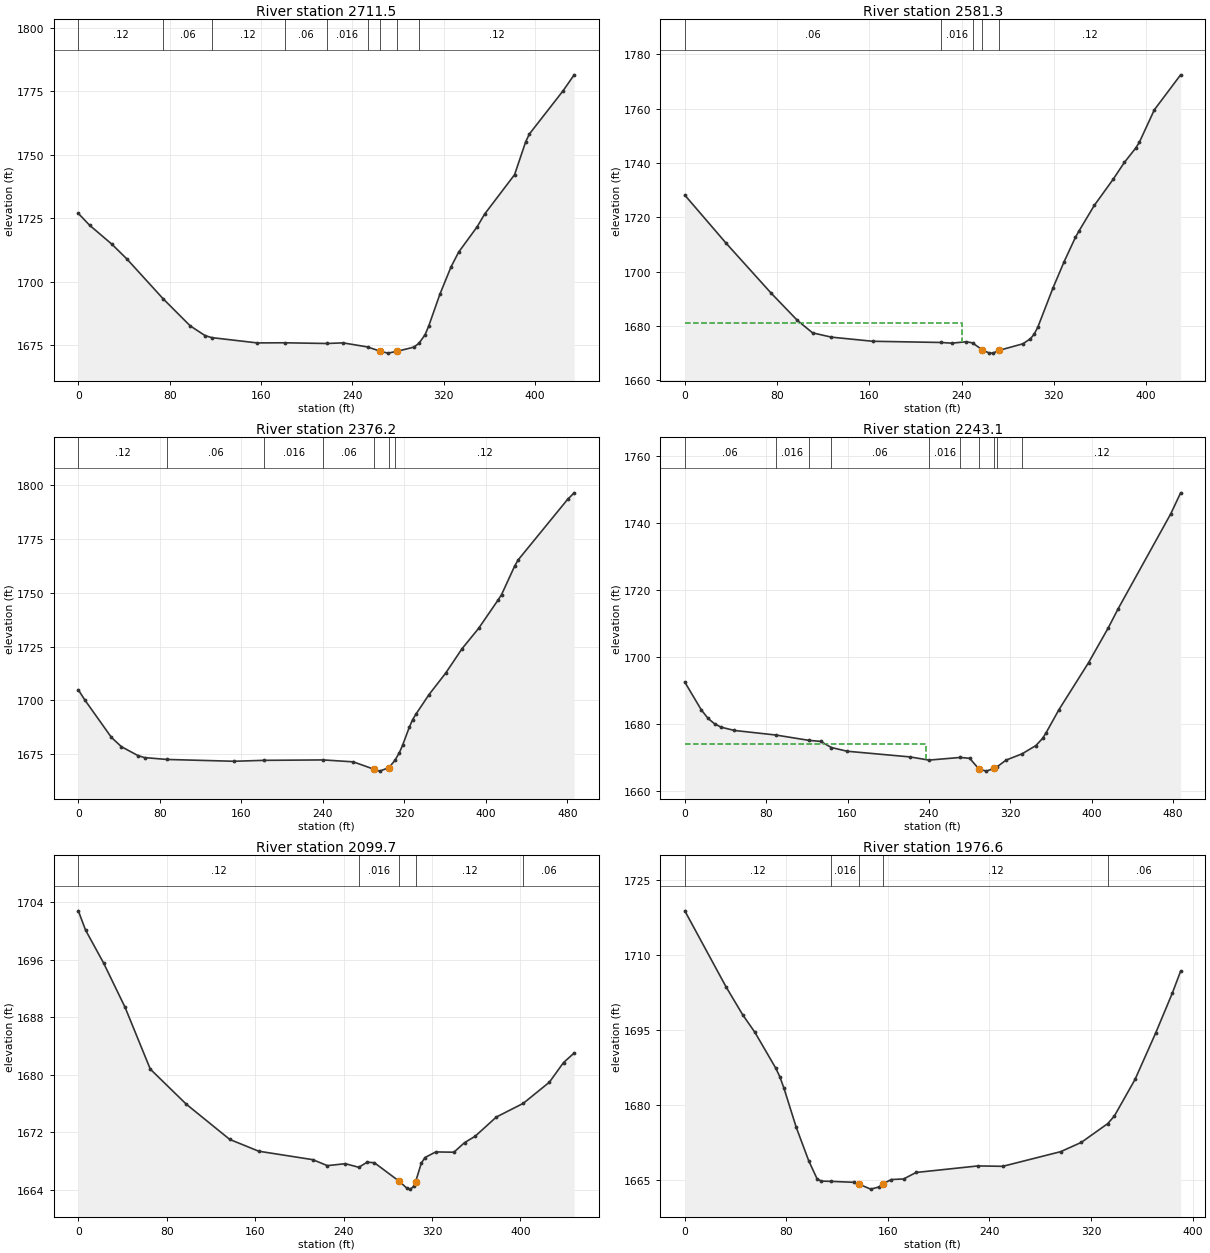
Type RM Length L Ch R = 1 ,2711.5  ,131,130.2,129.1
XS GIS Cut Line= 2
     2013622.136      221161.371     2013193.316      221091.926
#Sta/Elev= 30
       0 1726.93     9.8  1722.3    29.4  1714.8    42.5 1709.01   74.371693.291
      98 1682.67     111 1678.84  116.96 1678.03   156.8 1675.95  180.661676.004
  217.821675.723   231.9 1675.97  253.351674.366   264.2 1672.74   271.1 1671.93
   279.2 1672.63     294  1674.3   298.41675.794   303.8 1679.17     307 1682.63
   316.8 1695.17   326.6 1705.94   333.2 1711.69   349.5 1721.72     356 1726.68
   382.2 1742.17     392  1755.2   395.2  1758.2   424.6 1775.14   434.4 1781.47
#Mann= 9 ,-1 , 0
       0     .12       0   74.37     .06       0  116.96     .12       0
  180.66     .06       0  217.82    .016       0  253.35     .06       0
   264.2    .045       0   279.2     .06       0   298.4     .12       0
Bank Sta=264.2,279.2
XS Rating Curve= 0 ,0
Exp/Cntr=0.3,0.1

Type RM Length L Ch R = 1 ,2581.3  ,205.1,205.1,204.4
XS GIS Cut Line= 2
     2013646.441      221022.482     2013219.358      220972.135
#Sta/Elev= 30
       0  1728.2    35.8  1710.5    74.9 1692.08    97.7 1682.03   110.8 1677.47
   127.1 1675.89   162.9 1674.37  222.54 1673.92   231.3 1673.67   244.3 1674.19
  249.531673.763   257.8 1671.27   263.9 1670.05   267.2    1670   272.8 1671.04
   293.2 1673.44   299.7 1675.29     303 1676.97   306.2 1679.62   319.3    1694
     329 1703.72   338.8 1712.67   342.1 1715.16   355.1 1724.39   371.4 1733.98
   381.2 1740.23     391  1745.5   394.2 1747.66   407.2 1759.61     430  1772.5
#Mann= 5 ,-1 , 0
       0     .06       0  222.54    .016       0  249.53     .06       0
   257.8    .045       0   272.8     .12       0
#XS Ineff= 2 , 0
          240.77 1681.25
Permanent Ineff=
       F       F
Bank Sta=257.8,272.8
XS Rating Curve= 0 ,0
Exp/Cntr=0.3,0.1

Type RM Length L Ch R = 1 ,2376.2  ,125.8,133.1,139.3
XS GIS Cut Line= 4
     2013643.837      220873.176      2013405.99      220795.051
     2013306.164      220784.635     2013176.823      220826.301
#Sta/Elev= 30
       0 1704.88     6.5 1700.09    32.5 1682.78    42.3 1678.48    58.5 1674.35
      65 1673.41   86.881672.554   152.8 1671.71  182.471672.142  240.511672.329
   269.8 1671.44   289.8 1668.07   295.7 1667.13   304.8 1668.74  310.731672.157
   315.1 1675.76   318.3 1679.24   324.8 1687.49     328 1690.97   331.3 1693.58
   344.2 1702.71   360.4 1712.58   376.6 1724.01   392.8 1733.41   412.2 1746.79
   415.4 1749.16   428.4 1762.56   431.6  1765.2   480.1 1793.31   486.6 1796.38
#Mann= 7 ,-1 , 0
       0     .12       0   86.88     .06       0  182.47    .016       0
  240.51     .06       0   289.8    .045       0   304.8     .06       0
  310.73     .12       0
Bank Sta=289.8,304.8
XS Rating Curve= 0 ,0
Exp/Cntr=0.3,0.1

Type RM Length L Ch R = 1 ,2243.1  ,142.2,143.4,145.3
XS GIS Cut Line= 3
     2013648.178       220773.35     2013333.073      220640.538
     2013203.733      220707.378
#Sta/Elev= 30
       0 1692.47    16.3 1684.13    22.8 1681.64    29.3 1679.99    35.8 1678.98
    48.8 1678.01   89.461676.649  122.021675.049   133.5 1674.75  144.171672.905
   159.6  1671.8   221.4  1670.1  239.981669.146   270.8 1669.94   280.1 1669.68
   289.2 1666.49   296.4 1665.85   304.2 1666.67  307.231667.179   315.9 1669.15
  331.761671.044   345.2  1673.5   351.7 1675.62   354.9 1677.14   367.8  1684.2
     397 1698.29   416.4 1708.72   426.1 1714.42   477.8 1742.79   487.5 1749.06
#Mann= 10 ,-1 , 0
       0     .06       0   89.46    .016       0  122.02     .12       0
  144.17     .06       0  239.98    .016       0   270.8     .12       0
   289.2    .045       0   304.2     .12       0  307.23     .06       0
  331.76     .12       0
#XS Ineff= 2 , 0
          237.22 1674.01
Permanent Ineff=
       F       F
Bank Sta=289.2,304.2
XS Rating Curve= 0 ,0
Exp/Cntr=0.3,0.1

Type RM Length L Ch R = 1 ,2099.7  ,140.6,123.1,104.3
XS GIS Cut Line= 4
       2013682.9      220596.267     2013627.344      220630.121
     2013379.948      220503.385     2013281.858      220542.447
#Sta/Elev= 30
       0 1702.82     6.5 1700.15    22.8 1695.57    42.3 1689.38    65.1 1680.78
    97.8 1675.88     137 1670.99   163.2 1669.35   212.2 1668.17   225.3 1667.34
   241.6 1667.61  253.74 1667.11   261.3 1667.82   267.8 1667.75   290.2 1665.18
   297.2 1664.21   300.5 1664.07   303.8 1664.51   305.2 1665.13   310.3 1667.68
   313.6 1668.47   323.4 1669.25   339.8 1669.21   349.4 1670.54     359 1671.43
   378.2 1674.11  402.491676.007   426.2 1678.96     439  1681.7   448.6 1683.02
#Mann= 5 ,-1 , 0
       0     .12       0  253.74    .016       0   290.2    .045       0
   305.2     .12       0  402.49     .06       0
Bank Sta=290.2,305.2
XS Rating Curve= 0 ,0
Exp/Cntr=0.3,0.1

Type RM Length L Ch R = 1 ,1976.6  ,146.7,145.8,145.5
XS GIS Cut Line= 3
     2013600.435        220367.1     2013270.573      220467.794
     2013225.435      220474.739
#Sta/Elev= 30
       0 1718.78    32.5 1703.58    45.6    1698    55.3 1694.46    71.6 1687.35
    74.8 1685.65    78.1 1683.33    87.8 1675.49    97.6 1668.83   104.1 1665.26
   107.4 1664.74   115.5 1664.69   133.4  1664.5     137 1664.16   146.4 1663.14
   152.9 1663.56   156.2  1664.2   162.7 1665.06   172.4 1665.17   182.2 1666.47
     231 1667.78   250.5  1667.7   296.1 1670.63   312.4 1672.49   333.21676.245
   338.4 1677.76   354.7 1685.08     371 1694.39     384 1702.29   390.6 1706.72
#Mann= 5 ,-1 , 0
       0     .12       0   115.5    .016       0     137    .045       0
   156.2     .12       0   333.2     .06       0
Bank Sta=137,156.2
XS Rating Curve= 0 ,0
Exp/Cntr=0.3,0.1

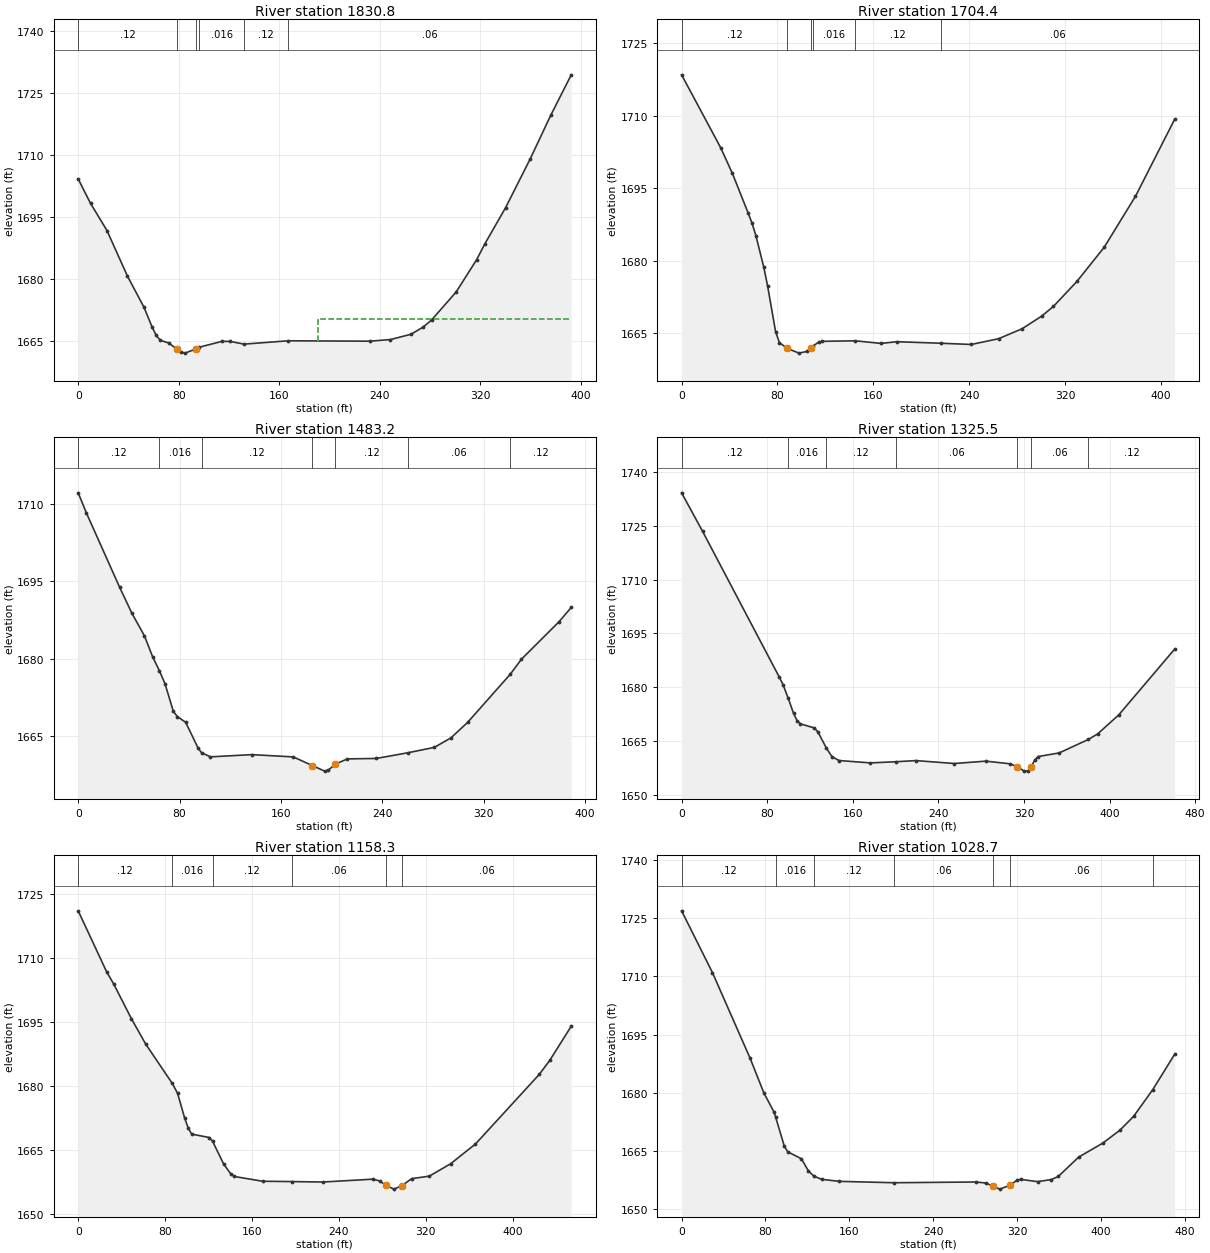
Type RM Length L Ch R = 1 ,1830.8  ,126.8,126.4,126
XS GIS Cut Line= 2
     2013524.914      220235.156     2013156.858       220371.44
#Sta/Elev= 30
       0 1704.16     9.8 1698.27    22.9 1691.68    39.2 1680.65    52.3 1673.16
    58.9 1668.29    62.1  1666.3    65.4 1665.11      72 1664.47    78.5    1663
    81.8 1662.27      85 1662.01   93.69 1663.02   96.18 1663.43   114.5 1664.86
     121 1664.84  132.05 1664.19  167.241664.997   232.2  1664.9   248.6  1665.3
   264.9 1666.57   274.7 1668.33   281.3 1670.03   300.9 1676.82   317.2 1684.63
   323.8  1688.5   340.2  1697.2   359.8    1709   376.1 1719.53   392.5 1729.37
#Mann= 6 ,-1 , 0
       0     .12       0    78.5    .045       0   93.69     .12       0
   96.18    .016       0  132.05     .12       0  167.24     .06       0
#XS Ineff= 2 , 0
                          190.91         1670.17
Permanent Ineff=
       F       F
Bank Sta=78.5,93.69
XS Rating Curve= 0 ,0
Exp/Cntr=0.3,0.1

Type RM Length L Ch R = 1 ,1704.4  ,221.6,221.2,213.4
XS GIS Cut Line= 2
     2013517.969      220104.079     2013134.289      220252.517
#Sta/Elev= 30
       0 1718.47    32.6  1703.4    42.4 1698.08    55.5 1689.92    58.8 1687.78
      62 1685.21    68.6 1678.67    71.8 1674.76    78.4 1665.41    81.6 1663.11
    88.2 1661.91      98 1660.94   104.5 1661.29   107.8 1661.94  109.661662.385
   114.3 1663.23   117.5 1663.38  144.791663.487   166.5 1662.95   179.6  1663.3
  216.231662.987   241.6 1662.73   264.5 1663.92   284.1 1665.98   300.4 1668.58
   310.2 1670.59   329.8 1675.75   352.6 1682.82   378.7 1693.36   411.4 1709.28
#Mann= 6 ,-1 , 0
       0     .12       0    88.2    .045       0   107.8     .12       0
  109.66    .016       0  144.79     .12       0  216.23     .06       0
Bank Sta=88.2,107.8
XS Rating Curve= 0 ,0
Exp/Cntr=0.3,0.1

Type RM Length L Ch R = 1 ,1483.2  ,155.4,157.7,165.8
XS GIS Cut Line= 4
     2013448.525      219937.413     2013269.705      219988.628
     2013257.553      220004.253     2013091.754      220082.378
#Sta/Elev= 30
       0 1712.19     6.5 1708.27    32.6 1693.92    42.4 1688.81    52.2 1684.49
    58.7 1680.41   64.041677.697    68.5 1675.17    75.1 1669.78    78.3 1668.77
    84.8 1667.68    94.6 1662.69   97.311661.778   104.4 1660.97   137.1  1661.4
   169.7 1660.96   184.8 1659.28   194.5  1658.2   197.3 1658.38     203 1659.56
   212.4 1660.57   235.3 1660.66  260.261661.767   281.1 1662.81   294.2 1664.66
   307.3 1667.65  341.041677.014   349.8 1679.91   379.3 1687.14   389.1 1689.96
#Mann= 7 ,-1 , 0
       0     .12       0   64.04    .016       0   97.31     .12       0
   184.8    .045       0     203     .12       0  260.26     .06       0
  341.04     .12       0
Bank Sta=184.8,203
XS Rating Curve= 0 ,0
Exp/Cntr=0.3,0.1

Type RM Length L Ch R = 1 ,1325.5  ,164.6,167.2,169.3
XS GIS Cut Line= 2
     2013457.205      219788.975     2013019.705       219933.94
#Sta/Elev= 30
       0 1734.12    19.6 1723.41    91.5 1682.74    94.8 1680.75   99.721676.928
   104.6 1672.79   107.9 1670.74   111.1 1669.84   124.2 1668.69   127.5 1667.56
  135.311663.111   140.6  1660.7   147.1 1659.64   176.5 1658.98  200.631659.309
     219 1659.62     255 1658.81   284.4 1659.47   307.3 1658.72   313.8  1657.9
   320.3 1656.69   323.6  1656.7   326.9 1657.94   330.1  1659.8   333.4 1660.75
     353 1661.76  380.351665.521     389 1667.07   408.6 1672.32   460.9 1690.64
#Mann= 7 ,-1 , 0
       0     .12       0   99.72    .016       0  135.31     .12       0
  200.63     .06       0   313.8    .045       0   326.9     .06       0
  380.35     .12       0
Bank Sta=313.8,326.9
XS Rating Curve= 0 ,0
Exp/Cntr=0.3,0.1

Type RM Length L Ch R = 1 ,1158.3  ,129.1,129.6,130.2
XS GIS Cut Line= 2
     2013409.462      219663.975     2012965.886      219761.197
#Sta/Elev= 30
       0 1721.11    26.1 1706.83    32.7 1703.92      49 1695.78    62.1 1689.84
   86.641680.568    91.5 1678.26      98 1672.47   101.3 1670.09   104.5 1668.66
   120.9 1667.85  123.84 1666.94   133.9 1661.66   140.5 1659.32   143.8  1658.7
   169.9 1657.58  196.591657.506   225.4  1657.4   271.2 1658.07   277.7 1657.66
   283.1 1656.66   290.8 1655.73   298.1 1656.54   307.1 1658.19   323.4 1658.78
     343 1661.69   365.9 1666.33   424.7  1682.7   434.5 1686.05   454.1 1694.01
#Mann= 6 ,-1 , 0
       0     .12       0   86.64    .016       0  123.84     .12       0
  196.59     .06       0   283.1    .045       0   298.1     .06       0
Bank Sta=283.1,298.1
XS Rating Curve= 0 ,0
Exp/Cntr=0.3,0.1

Type RM Length L Ch R = 1 ,1028.7  ,163.7,157.5,147.8
XS GIS Cut Line= 2
     2013409.462      219539.843     2012947.657      219629.253
#Sta/Elev= 30
       0 1726.92    29.4 1710.99    65.3 1688.92    78.4 1679.99    88.2 1674.98
   89.66 1673.75      98 1666.18   101.3 1664.74   114.3 1662.94   120.9 1659.84
  126.251658.439   133.9 1657.63   150.3 1657.12  202.48 1656.76   280.9 1656.95
   290.7 1656.67   297.2 1655.81   303.8 1655.11   313.6 1656.18   320.1 1657.44
   323.4 1657.63   339.7 1657.04   352.8 1657.59   359.3 1658.37   378.9 1663.39
   401.8 1666.97   418.1  1670.3   431.2 1673.87  449.511680.785   470.4 1689.91
#Mann= 7 ,-1 , 0
       0     .12       0   89.66    .016       0  126.25     .12       0
  202.48     .06       0   297.2    .045       0   313.6     .06       0
  449.51     .12       0
Bank Sta=297.2,313.6
XS Rating Curve= 0 ,0
Exp/Cntr=0.3,0.1

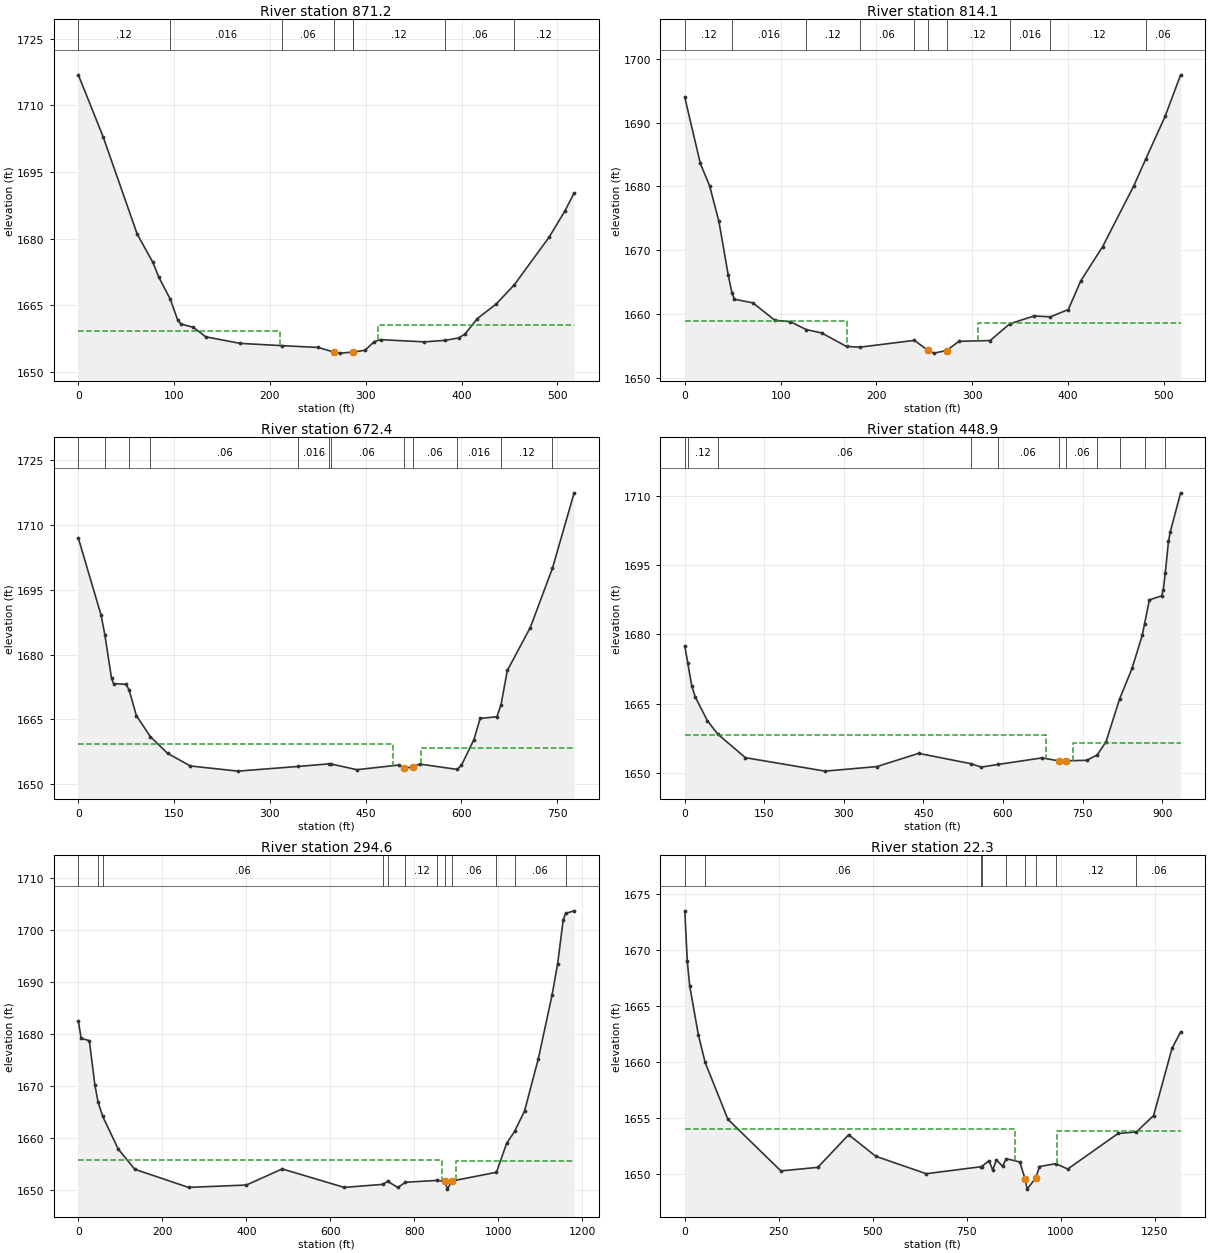
Type RM Length L Ch R = 1 ,871.2   ,54.9,57.1,61.3
XS GIS Cut Line= 3
      2013410.33      219408.767     2013332.205      219377.517
     2012931.164      219541.579
#Sta/Elev= 30
       0 1716.87    25.9 1702.91    61.5 1680.96    77.7 1674.66    84.1 1671.25
   95.971666.342   103.7 1661.65     107 1660.76     120 1660.02     133 1657.87
   168.8  1656.4  212.871655.875   250.3 1655.48   266.6 1654.44   273.1  1654.2
   286.1 1654.43  286.24 1654.43   299.2 1654.85   308.9  1656.8   315.4 1657.23
   361.1 1656.74     3831657.082   396.9 1657.63   403.4 1658.48   416.4 1661.99
     436 1665.25  455.141669.641   491.4 1680.36   507.7 1686.21   517.4 1690.25
#Mann= 8 ,-1 , 0
       0     .12       0   95.97    .016       0  212.87     .06       0
   266.6    .045       0   286.1    .016       0  286.24     .12       0
     383     .06       0  455.14     .12       0
#XS Ineff= 2 , 0
          210.51 1659.27  312.78         1660.52
Permanent Ineff=
       F       F
Bank Sta=266.6,286.1
XS Rating Curve= 0 ,0
Exp/Cntr=0.3,0.1

Type RM Length L Ch R = 1 ,814.1   ,145.8,141.7,137.2
XS GIS Cut Line= 3
     2013384.289      219361.024     2013306.164      219329.774
     2012905.122      219493.836
#Sta/Elev= 30
       0 1693.93    16.2 1683.58    25.9 1680.08    35.6  1674.5    45.3 1666.12
   49.291663.261    51.8 1662.31    71.2 1661.74    93.9 1659.02   110.2 1658.79
  126.791657.557   142.8 1657.03   168.8 1654.91  182.931654.809  239.521655.869
   253.6 1654.33   260.1 1653.87   273.2 1654.28   286.1 1655.72   318.7 1655.84
  338.951658.451   364.3 1659.69  381.541659.557   400.2  1660.7   413.2 1665.19
     436 1670.55   468.6 1680.11  481.111684.322   501.2 1690.96   517.4 1697.47
#Mann= 10 ,-1 , 0
       0     .12       0   49.29    .016       0  126.79     .12       0
  182.93     .06       0  239.52     .12       0   253.6    .045       0
   273.2     .12       0  338.95    .016       0  381.54     .12       0
  481.11     .06       0
#XS Ineff= 2 , 0
          168.75 1658.92  305.97         1658.54
Permanent Ineff=
       F       F
Bank Sta=253.6,273.2
XS Rating Curve= 0 ,0
Exp/Cntr=0.3,0.1

Type RM Length L Ch R = 1 ,672.4   ,226.6,223.5,219.1
XS GIS Cut Line= 3
     2013496.811      219258.639     2013281.967      219137.111
     2012838.455      219426.996
#Sta/Elev= 30
       0 1707.02    35.7  1689.1   41.591684.585      52 1674.53    55.2  1673.3
    74.7 1673.13   79.521671.842    90.9 1665.89  112.761661.035   139.7 1657.16
   175.4 1654.23   250.1 1653.03  344.77 1654.12  392.061654.706  395.58 1654.69
   436.5 1653.36   501.9 1654.44   509.5 1653.72   524.5 1653.98   534.6 1654.67
  593.331653.433   600.1 1654.36   619.7 1660.35   629.5 1665.23   655.7 1665.63
  662.161668.435     672 1676.34     708 1686.29  742.631699.994   776.7 1717.48
#Mann= 12 ,-1 , 0
       0     .12       0   41.59    .016       0   79.52     .12       0
  112.76     .06       0  344.77    .016       0  392.06     .12       0
  395.58     .06       0   509.5    .045       0   524.5     .06       0
  593.33    .016       0  662.16     .12       0  742.63     .06       0
#XS Ineff= 2 , 0
          493.18 1659.27   537.5         1658.38
Permanent Ineff=
       F       F
Bank Sta=509.5,524.5
XS Rating Curve= 0 ,0
Exp/Cntr=0.3,0.1

Type RM Length L Ch R = 1 ,448.9   ,154.3,154.2,153.7
XS GIS Cut Line= 3
     2013512.002      219163.153     2013110.572      218937.713
      2012760.33      219257.725
#Sta/Elev= 30
       0 1677.51    5.591673.802    13.1 1668.88    19.6 1666.49    42.4 1661.34
   62.231658.409   114.3  1653.3   264.5 1650.39   362.4 1651.38   440.8 1654.24
  540.421651.981   558.6 1651.25  590.311651.832   673.1 1653.25  704.68 1652.63
   718.9 1652.62   758.1 1652.74   777.51653.897   794.1 1656.75  819.851666.045
   843.2 1672.64   862.8 1679.96  866.711682.273   875.9 1687.48   898.8 1688.35
   902.1 1689.61   905.81693.231   911.9 1700.16   915.2 1702.19   934.8 1710.67
#Mann= 11 ,-1 , 0
       0    .016       0    5.59     .12       0   62.23     .06       0
  540.42    .016       0  590.31     .06       0  704.68    .045       0
   718.9     .06       0   777.5    .016       0  819.85     .06       0
  866.71    .016       0   905.8     .12       0
#XS Ineff= 2 , 0
          681.82 1658.11  731.53         1656.42
Permanent Ineff=
       F       F
Bank Sta=704.68,718.9
XS Rating Curve= 0 ,0
Exp/Cntr=0.3,0.1

Type RM Length L Ch R = 1 ,294.6   ,252.2,272.3,291.4
XS GIS Cut Line= 3
     2013570.596      219152.302     2013021.551       218811.59
     2012630.926      219176.174
#Sta/Elev= 30
       0 1682.47     6.6 1679.13    26.2 1678.68    39.4 1670.14   47.261666.796
   58.111664.117    95.1 1657.83   134.5 1653.96   262.4 1650.48   400.2 1650.94
   485.4 1654.03     633 1650.48  724.471651.064  736.39 1651.64   760.9 1650.47
  778.781651.469  854.78 1651.83   872.4 1651.63   878.9 1650.15   888.8  1651.7
   995.51653.388  1019.9 1658.98 1038.68 1661.23  1062.5  1665.2  1095.3 1675.24
    1128 1687.48  1141.2 1693.46  1154.3  1701.8 1159.921703.124  1180.5 1703.62
#Mann= 12 ,-1 , 0
       0    .016       0   47.26     .12       0   58.11     .06       0
  724.47     .12       0  736.39    .016       0  778.78     .12       0
  854.78     .06       0   872.4    .045       0   888.8     .06       0
   995.5    .016       0 1038.68     .06       0 1159.92    .016       0
#XS Ineff= 2 , 0
           864.8 1655.67   898.3         1655.58
Permanent Ineff=
       F       F
Bank Sta=872.4,888.8
XS Rating Curve= 0 ,0
Exp/Cntr=0.3,0.1

Type RM Length L Ch R = 1 ,22.3    ,14.8,22.3,29.3
XS GIS Cut Line= 4
     2013581.447      219111.069     2013025.891      218757.337
     2012657.466      218725.173     2012415.278      218885.329
#Sta/Elev= 30
       0 1673.53     6.6 1669.02    13.1 1666.81      36 1662.44   54.121659.958
   114.7 1654.87   255.6 1650.25   353.9 1650.57   435.8 1653.49   507.9 1651.56
   642.2    1650  787.861650.625  789.411650.639   809.2 1651.16     819 1650.33
   828.8 1651.24   845.2 1650.67   855.11651.341     891 1651.05     905 1649.54
   910.6 1648.62   933.5 1649.63   943.3 1650.64  986.851650.896  1018.6 1650.42
  1152.4  1653.6 1201.32 1653.74    1247 1655.21    1296 1661.23  1318.8 1662.69
#Mann= 9 ,-1 , 0
       0     .12       0   54.12     .06       0  787.86     .12       0
  789.41    .016       0   855.1     .07       0     905    .045       0
   933.5     .07       0  986.85     .12       0 1201.32     .06       0
#XS Ineff= 2 , 0
          878.98 1653.98  990.34         1653.79
Permanent Ineff=
       F       F
Bank Sta=905,933.5
XS Rating Curve= 0 ,0
Exp/Cntr=0.3,0.1

Chan Stop Cuts=-1
Use User Specified Reach Order=0
Composite Channel Slope=5